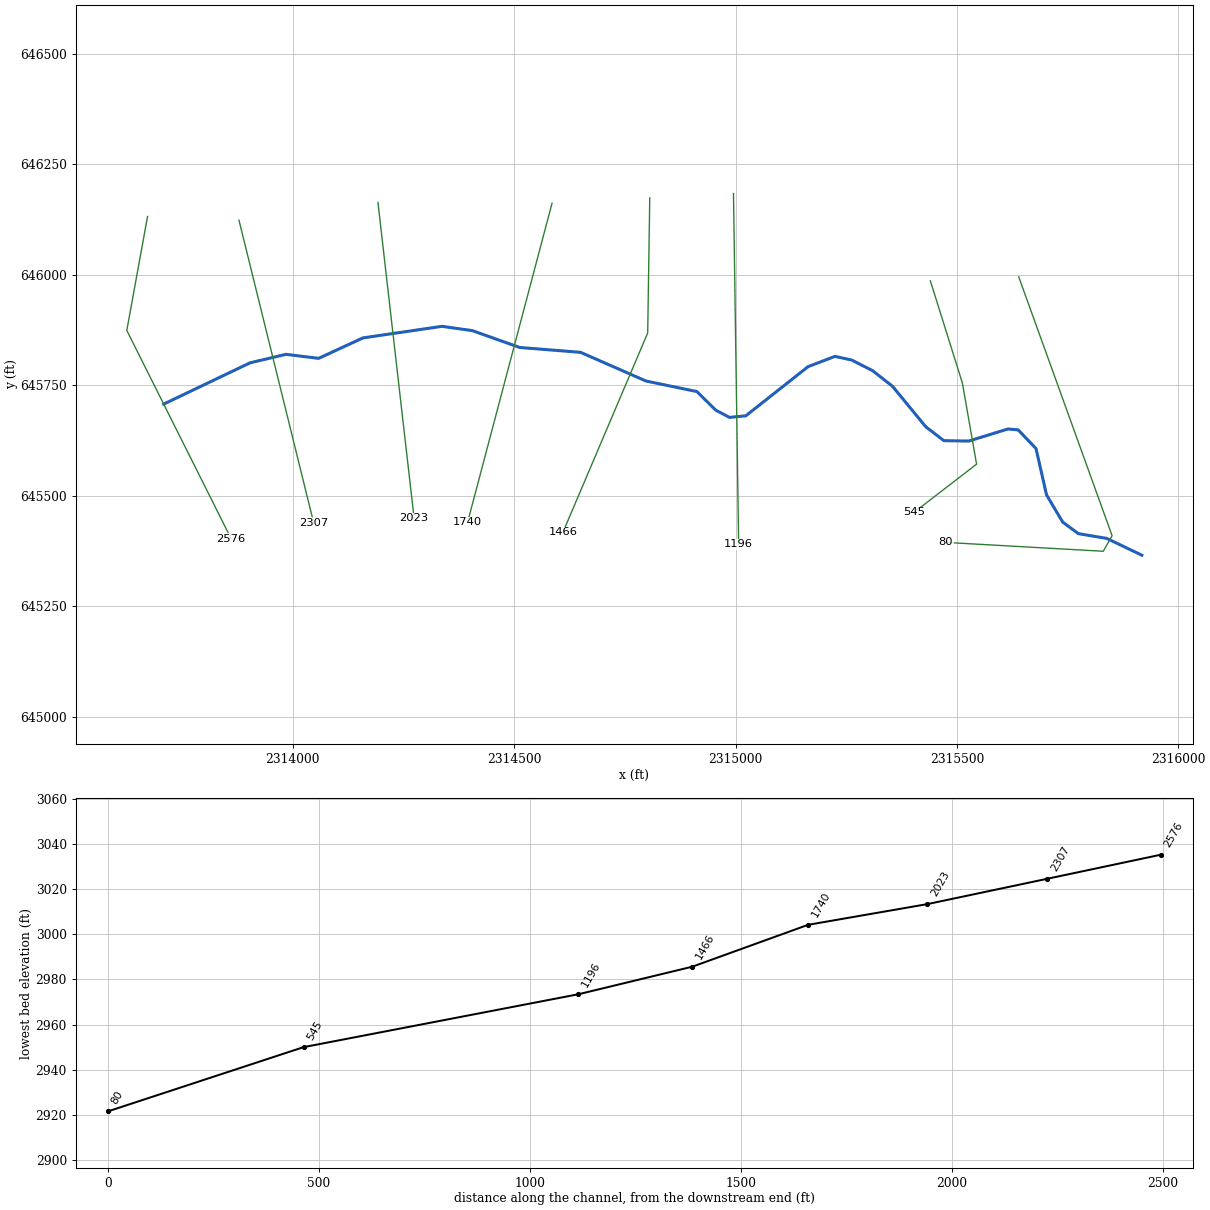
--- REDRN_1DS.prj (project) ---

Proj Title=REDRN_1DS
Current Plan=p01
Default Exp/Contr=0,0
English Units
Geom File=g01
Flow File=f01
Plan File=p01
BEGIN DESCRIPTION:
----------MODEL BY WOOD PLC 2022----------
AFH study
Randolph County, WV
HEC-RAS Version: RAS 6.2
Vertical Datum: NAVD88
Projection: NAD 1983 StatePlane West Virginia S FIPS 4702 (US Feet)
Terrain: 1-meter LIDAR (FEMA Region III 3DEP collected 2016-2018)
Land Use: 2019 NLCD
Hydrologic Method:
WV SIR2010-5033 regression equations
Additional Model Notes:
None
END DESCRIPTION:
DSS Export Rating Curves= 0
DSS Export Rating Curve Sorted= 0
DSS Export Volume Flow Curves= 0
DXF OffsetX= 0
DXF OffsetY= 0
DXF ScaleX= 0
DXF ScaleY= 0

--- REDRN_1DS.p01 (plan) ---

Plan Title=Floodplain
Program Version=6.20
Short Identifier=Floodplain
Geom File=g01
Flow File=f01
Subcritical Flow
K Sum by GR= 0
Std Step Tol= 0.01
Critical Tol= 0.01
Num of Std Step Trials= 20
Max Error Tol= 0.3
Flow Tol Ratio= 0.001
Split Flow NTrial= 30
Split Flow Tol= 0.02
Split Flow Ratio= 0.02
Log Output Level= 0
Friction Slope Method= 1
Unsteady Friction Slope Method= 2
Unsteady Bridges Friction Slope Method= 1
Parabolic Critical Depth
Global Vel Dist= 0 , 0 , 0
Global Log Level= 0
CheckData=True
Encroach Param=-1 ,0,0, 0
Mapping Interval=1HOUR
Computation Time Step Use Courant=        0
Computation Time Step Use Time Series=    0
Computation Time Step Count To Double=0
Computation Time Step Max Doubling=0
Computation Time Step Max Halving=0
Computation Time Step Residence Courant=0
Run HTab= 0
Run UNet= 0
Run Sediment= 0
Run PostProcess= 0
Run WQNet= 0
Run RASMapper=-1
UNET Theta= 0
UNET Theta Warmup= 0
UNET ZTol= 0
UNET ZSATol= 0
UNET MxIter= 0
UNET Max Iter WO Improvement= 0
UNET MaxInSteps= 0
UNET DtIC= 0
UNET DtMin= 0
UNET MaxCRTS= 0
UNET WFStab= 0
UNET SFStab= 0
UNET WFX= 1
UNET SFX= 1
UNET Gravity=32.174
UNET 1D Methodology=Finite Difference
UNET DSS MLevel= 1
UNET Pardiso=0
UNET DZMax Abort= 0
UNET Use Existing IB Tables= 0
UNET Froude Reduction=False
UNET Froude Limit= 0
UNET Froude Power= 0
UNET D1 Cores= 0
UNET WindReference=Eulerian
UNET WindDragFormulation=Hsu (1988)
UNET D2 Coriolis=0
UNET D2 Cores= 0
UNET D2 Theta= 1
UNET D2 Theta Warmup= 1
UNET D2 Z Tol= 0.01
UNET D2 Volume Tol= 0.01
UNET D2 Max Iterations= 20
UNET D2 Equation= 0
UNET D2 RampUpFraction=0.1
UNET D2 TimeSlices= 1
UNET D2 Turbulence Formulation=Non-Conservative (original)
UNET D2 Eddy Viscosity=0.3
UNET D2 Transverse Eddy Viscosity=0.1
UNET D2 Smagorinsky Mixing=0
UNET D2 BCVolumeCheck=0
UNET D2 Cores=0
UNET D2 SolverType=PARDISO (Direct)
UNET D2 Minimum Iterations= 2147483647
UNET D2 Maximum Iterations= 2147483647
UNET D2 Restart Number= 10
UNET D2 Relaxation Coeff=1.3
UNET D2 SOR Precondition Iterations= 10
UNET D2 ILUT Maximum Fill= 8
UNET D2 ILUT Tolerance=1E-08
UNET D1D2 MaxIter= 0
UNET D1D2 ZTol=0.01
UNET D1D2 QTol=0.1
UNET D1D2 MinQTol=1
Write IC File= 0
Write IC File at Fixed DateTime=0
Write IC File at Sim End=0
Echo Input=False
Echo Parameters=False
Echo Output=False
Write Detailed= 0
HDF Write Warmup=0
HDF Write Time Slices=0
HDF Flush=0
HDF Compression= 1
HDF Chunk Size= 1
HDF Spatial Parts= 1
HDF Use Max Rows=0
HDF Fixed Rows= 1
Calibration Method= 0
Calibration Iterations= 20
Calibration Max Change=0.05
Calibration Tolerance=0.2
Calibration Maximum=1.5
Calibration Minimum=0.5
Calibration Optimization Method= 1
WQ AD Non Conservative
WQ ULTIMATE=-1
WQ Max Comp Step=1HOUR
WQ Output Interval=15MIN
WQ Output Selected Increments= 0
WQ Output face flow=0
WQ Output face velocity=0
WQ Output face area=0
WQ Output face dispersion=0
WQ Output cell volume=0
WQ Output cell surface area=0
WQ Output cell continuity=0
WQ Output cumulative cell continuity=0
WQ Output face conc=0
WQ Output face dconc_dx=0
WQ Output face courant=0
WQ Output face peclet=0
WQ Output face adv mass=0
WQ Output face disp mass=0
WQ Output cell mass=0
WQ Output cell source sink temp=0
WQ Output nsm pathways=0
WQ Output nsm derived pathways=0
WQ Create Restart=0
WQ Fixed Restart=0
WQ System Summary=0
WQ Write To DSS=0
Sorting and Armoring Iterations= 10
XS Update Threshold= 0.02
Bed Roughness Predictor= 0
Hydraulics Update Threshold= 0.02
Energy Slope Method= 1
Volume Change Method= 1
Sediment Retention Method= 0
Sediment TS Multiplier= 1
Warm Up Method= 0
XS Weighting Method= 0
Number of US Weighted Cross Sections= 1
Number of DS Weighted Cross Sections= 1
Upstream XS Weight=0
Main XS Weight=1
Downstream XS Weight=0
Number of DS XS's Weighted with US Boundary= 1
Upstream Boundary Weight= 1
Weight of XSs Associated with US Boundary= 0
Number of US XS's Weighted with DS Boundary= 1
Downstream Boundary Weight= 0.5
Weight of XSs Associated with DS Boundary= 0.5
Percentile Method= 0
Sediment Output Level= 3
Mass or Volume Output= 0
Output Increment Type= 1
Profile and TS Output Increment= 1
Transport Output Increment 1
XS Output Flag= 0
XS Output Increment= 10
Read HDF5 Sediment Hotstart= 0
Sediment Hotstart Type= 0
Write Gradation File= 0
Read Gradation Hotstart= 0
Write HDF5 File= 1
Write Binary Output= 1
Write DSS Sediment File= 0
DSS Sediment Output Type= 1
SV Curve= 0
Specific Gage Flag= 0
Subcell Erosion Methods= 0
Subcell Deposition Methods= 0
Advection Scheme= 1
Matrix Solver= 0
Implicit Weighting Factor= 1
Maximum Outer Loop Convergence Iterations= 5
Convergence Maximum Absolute= 0.001
Convergence RMSE= 0.0001
Grain Fractions Max Abs Error= 0.001
Max Subgrid Regions= 1
Max Subgrid Length Scale= 3.402823E+38
Initial Layer Thickness= 3.402823E+38
Min Layer Thickness= 3.402823E+38
Max Layer Thickness= 3.402823E+38
Number of Layers= 5

--- REDRN_1DS.f01 (steady flow) ---

Flow Title=Flow
Program Version=6.20
Number of Profiles= 1
Profile Names=P100yr
River Rch & RM=REDRN_1DS,Main            ,2576
     715
Boundary for River Rch & Prof#=REDRN_1DS,Main            , 1
Up Type= 0
Dn Type= 3
Dn Slope=0.06202
DSS Import GetInterval= 0
DSS Import GetPeak= 0
DSS Import FillOption= 0

--- REDRN_1DS.g01 (geometry) ---

Geom Title=Geometry
Program Version=6.20

River Reach=REDRN_1DS       ,Main
Reach XY= 30
2313708.15725239 645707.270851152313903.20799999645800.660999998
2313984.22099999645819.8880000112314058.29300003645810.850000009
2314158.28400002645857.0850000082314336.91700003645883.293000013
     2314405.355 645873.615000012314512.48474668645835.448866725
     2314649.994645824.416999996     2314797.809645759.503000021
2314912.78900003645735.5890000022314955.33400002645693.586999998
2314986.27200001645677.2160000062315023.08300003645680.624000013
     2315163.948645792.0559999942315224.82099998645815.305000022
     2315262.443645806.9850000142315309.59800005645783.057999998
2315354.69800001645747.6219999942315429.93200001645655.856000021
2315470.75700003645624.4759999962315527.07151988645623.611941029
2315615.51500005645650.945999995      2315638.59645648.881000012
2315678.91500001645606.6050000042315702.69000001645501.731999993
2315739.16599998645440.1500000062315774.61700003645414.012999997
2315838.71700002645403.2520000192315918.06000003645365.182999998

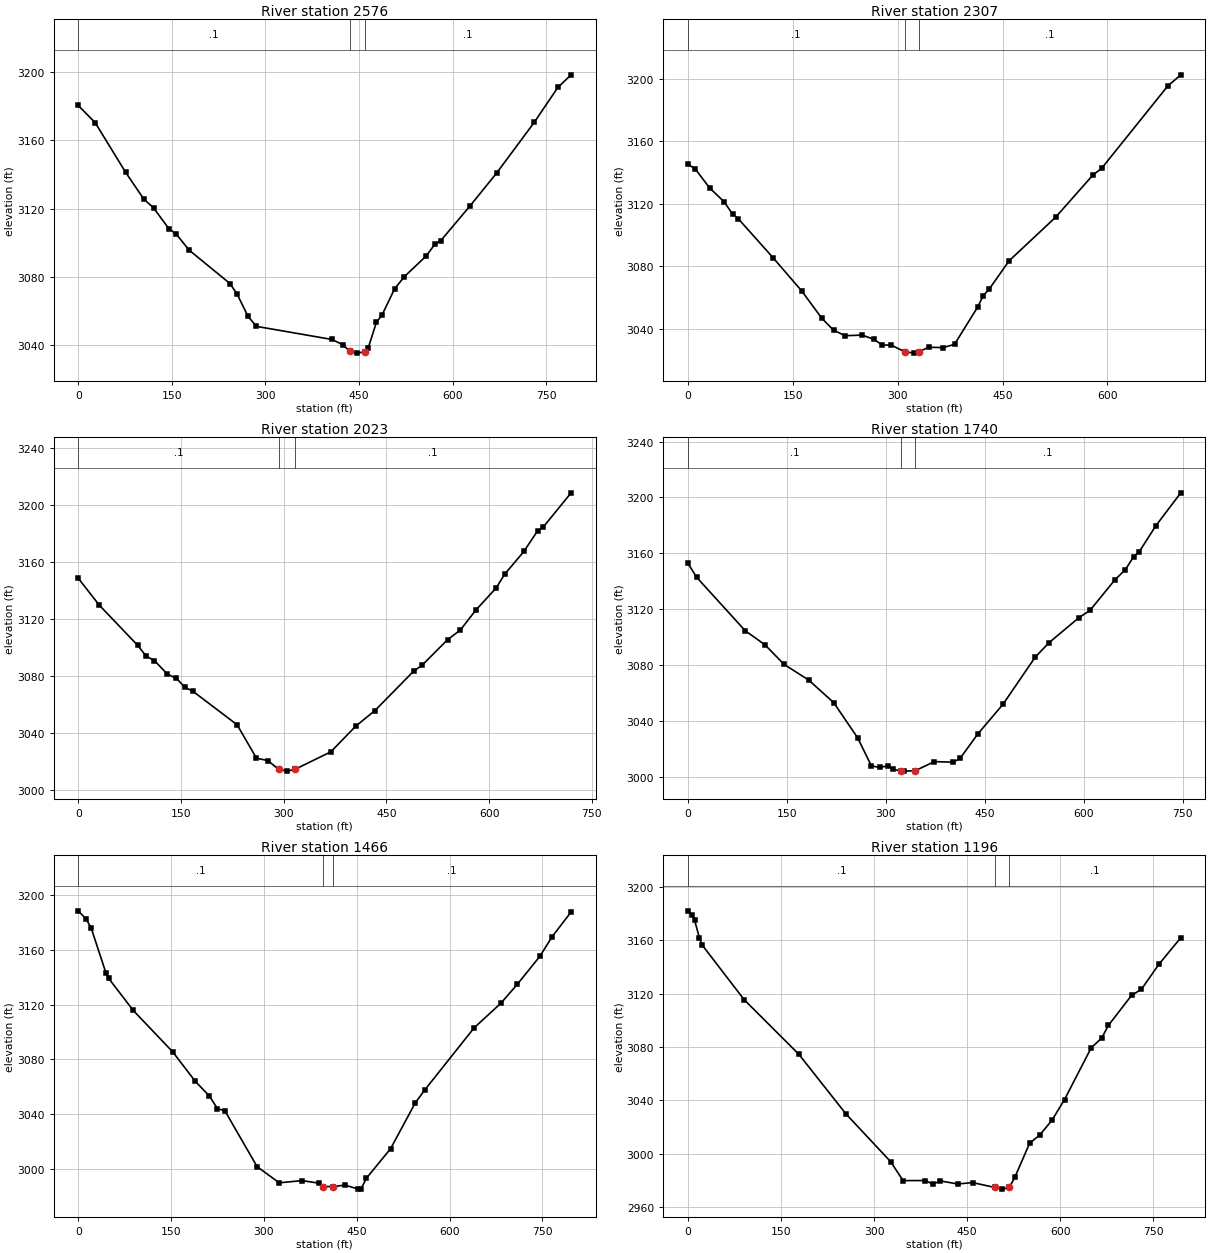
Type RM Length L Ch R = 1 ,2576    ,271.4,269.3,266.6
XS GIS Cut Line= 3
2313671.68253824646131.9018663142313624.79165998645874.002035879
2313860.62519476645402.334966313
#Sta/Elev= 30
       0 3180.51    27.2 3170.41    75.9 3141.31   105.1 3125.56   120.7 3120.42
   145.1 3108.28   157.3 3104.96   177.6 3095.65   243.2 3076.01   254.8 3069.64
     272  3056.8   285.4 3050.92   406.2 3043.25     424 3040.12   435.2  3036.2
   447.1 3035.22   459.8 3036.12   464.3 3037.95   477.7 3053.38   486.7 3057.61
   506.8 3072.98   522.4 3080.07   557.4 3092.21   571.6 3099.27   580.6 3101.15
   627.5 3121.52     670 3140.74   730.4 3170.56   768.4 3191.15   789.5 3198.45
#Mann= 3 ,-1,0
       0      .1       0   435.2    .045       0   459.8      .1       0
Bank Sta=435.2,459.8
XS Rating Curve= 0 ,0
Exp/Cntr(USF)=0,0
Exp/Cntr=0.3,0.1

Type RM Length L Ch R = 1 ,2307    ,285,284.5,281.7
XS GIS Cut Line= 2
 2313878.2471351646123.437346183  2314046.853757645439.055693412
#Sta/Elev= 30
       0 3145.39    10.6 3142.31    31.2 3130.14    51.8 3121.34    64.1 3113.37
    72.4 3110.33   121.8 3085.59     163 3064.21   191.8 3046.72   208.3 3039.26
   224.8  3035.7   249.5 3036.08     266 3033.37   278.3 3029.68   290.7 3029.75
  309.853025.488   323.7 3024.56   330.7 3025.52   344.3 3028.31   364.9  3028.1
   381.3 3030.17   414.3 3053.93   422.5  3061.4   430.8 3065.41   459.5 3083.66
   525.7 3111.37   579.1 3138.36   591.8 3142.78   686.2 3195.32   704.8 3202.48
#Mann= 3 ,-1,0
       0      .1       0  309.85    .045       0   330.7      .1       0
Bank Sta=309.85,330.7
XS Rating Curve= 0 ,0
Exp/Cntr(USF)=0,0
Exp/Cntr=0.3,0.1

Type RM Length L Ch R = 1 ,2023    ,286,282.6,277.6
XS GIS Cut Line= 2
2314192.20475838  646163.76537962314273.93177932645448.653946427
#Sta/Elev= 30
       0 3148.71    30.8 3129.77    87.1 3101.46    99.2 3094.01   111.3 3090.86
   130.2  3081.4   143.5 3078.37   155.6 3072.23   167.7 3069.29   232.1 3045.83
   260.3  3022.4   276.9 3020.75   292.5 3014.65   304.6 3013.33   316.6 3014.59
   316.6  3014.6     369 3026.89   405.2 3044.84   433.4 3055.86   490.1 3083.57
   501.8 3087.43   539.3 3105.51   558.2 3112.39   580.4 3126.14   610.5 3141.92
   622.6 3151.37   650.8 3167.41   670.9 3181.95     679  3184.5   719.8 3208.56
#Mann= 3 ,-1,0
       0      .1       0   292.5    .045       0   316.6      .1       0
Bank Sta=292.5,316.6
XS Rating Curve= 0 ,0
Exp/Cntr(USF)=0,0
Exp/Cntr=0.3,0.1

Type RM Length L Ch R = 1 ,1740    ,275,274.2,272.8
XS GIS Cut Line= 2
2314585.51604663 646162.062733332314394.81966445 645440.14071508
#Sta/Elev= 30
       0 3153.01    13.3 3142.91    86.9 3104.67   116.8 3094.58   145.8 3080.55
     183 3069.37   221.1 3053.12   257.1 3028.09   278.1 3007.91   290.5  3006.8
   302.9 3007.94   311.2 3005.36   323.6 3004.32   327.8 3004.16   344.3  3004.4
   373.3 3010.95   402.2 3010.58   412.5 3013.32   439.5 3030.92   477.3 3051.93
   526.3  3085.8     547 3096.02   592.5 3114.03   609.1 3119.15   646.5 3140.84
   662.9 3148.43   675.3 3157.62   683.6 3161.03   708.7 3179.62   746.7 3203.34
#Mann= 3 ,-1,0
       0      .1       0   323.6    .045       0   344.3      .1       0
Bank Sta=323.6,344.3
XS Rating Curve= 0 ,0
Exp/Cntr(USF)=0,0
Exp/Cntr=0.3,0.1

Type RM Length L Ch R = 1 ,1466    ,263.6,269.7,273.3
XS GIS Cut Line= 3
2314806.29017731646174.1891248682314801.61899413645868.226626515
2314610.05610747645416.887565205
#Sta/Elev= 30
       0 3188.19      13 3182.11      21 3175.65      45 3142.73      49 3139.17
      89 3115.65   152.8 3085.48     189 3064.17   211.9 3053.43     225  3044.2
     237 3042.63     289 3002.02   324.7 2990.22   361.5 2991.83   388.7 2989.98
  395.142987.488   412.1  2987.5     431 2988.56   452.7 2985.63   457.1 2986.04
   465.7 2993.62   504.7  3015.1   544.3 3048.24   559.6 3057.71   639.6 3103.01
     683 3121.03   709.1 3134.58   745.7 3155.01   765.6 3169.32   796.3  3187.4
#Mann= 3 ,0,0
       0      .1       0  395.14    .045       0   412.1      .1       0
Bank Sta=395.14,412.1
XS Rating Curve= 0 ,0
Exp/Cntr(USF)=0,0
Exp/Cntr=0.3,0.1

Type RM Length L Ch R = 1 ,1196    ,649.7,651.5,649.7
XS GIS Cut Line= 2
 2314995.4287199646183.9682468572315007.10667785645389.867106095
#Sta/Elev= 30
       0 3182.17     6.8 3179.41    10.8 3175.33    18.8 3161.65    23.2 3156.46
    90.8  3115.5   178.8 3074.61   254.8 3029.83   326.8 2994.02   346.8 2979.83
   382.8 2979.89   394.8 2977.14   406.8 2979.58   434.8 2977.31   458.8 2978.33
   494.8 2974.68   506.8 2973.44  517.822974.668   526.8 2982.26   550.8 3007.96
   566.9 3013.95   586.9 3025.22   606.9 3040.63     650 3079.49   666.9 3086.76
   677.6 3096.24   714.9 3118.74   730.9 3123.38   758.9 3142.03   794.2 3161.98
#Mann= 3 ,-1,0
       0      .1       0   494.8    .045       0  517.82      .1       0
Bank Sta=494.8,517.82
XS Rating Curve= 0 ,0
Exp/Cntr(USF)=0,0
Exp/Cntr=0.3,0.1

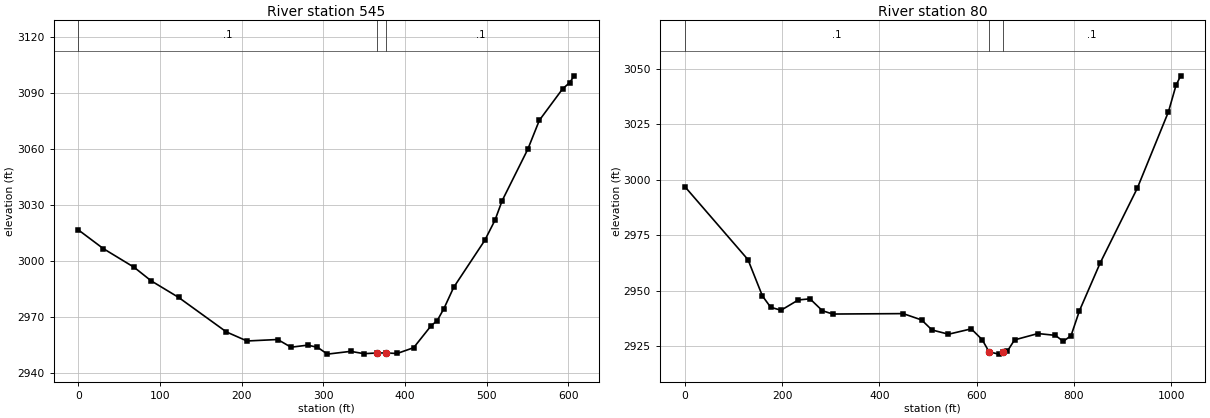
Type RM Length L Ch R = 1 ,545     ,468.8,464.2,466.7
XS GIS Cut Line= 4
2315440.19677934 645986.318007162315512.50796328645755.200470839
2315544.63160149645571.3079293842315403.40820343645462.216786591
#Sta/Elev= 30
       0 3016.63    30.5 3006.62    68.3 2996.58    89.2 2989.31   122.7 2980.46
   181.4  2961.9   206.6 2957.06   244.2 2957.85   260.5 2953.72   280.8 2954.82
   292.9 2953.69   305.1 2950.01   333.6  2951.5   349.8 2950.25     366 2950.63
  377.35 2950.63   390.4 2950.35   410.7 2953.46   432.3 2965.34   439.5 2967.93
   447.8 2974.45   459.7 2985.79   497.8 3011.01   510.3  3021.8   519.1  3032.3
   550.5 3059.85   564.7 3075.42   593.2 3092.28   601.8 3095.58   607.3 3099.24
#Mann= 3 ,-1,0
       0      .1       0     366    .045       0  377.35      .1       0
Bank Sta=366,377.35
XS Rating Curve= 0 ,0
Exp/Cntr(USF)=0,0
Exp/Cntr=0.3,0.1

Type RM Length L Ch R = 1 ,80      ,,,
XS GIS Cut Line= 4
 2315639.8636239 645995.359730132315850.79502943645409.389086167
2315830.82612556645374.1243590152315475.21120133645394.175382829
#Sta/Elev= 30
       0 2996.94   129.9 2964.06   159.6 2947.71   176.6 2942.62   197.9 2941.29
   233.3 2945.91   257.4 2946.43   282.9 2941.07   304.2 2939.58     449 2939.77
     487 2936.91   508.2 2932.42   542.2  2930.5     589 2932.91   611.5 2928.04
  625.57 2922.59   645.4 2921.54   655.2 2922.58   663.3  2922.9     678 2927.94
   726.1  2930.8   762.1 2929.98   778.1 2927.28   794.2 2929.85   811.5 2941.08
   853.9 2962.47   930.4  2996.2   994.5 3030.61    1010 3042.48  1019.5 3046.77
#Mann= 3 ,-1,0
       0      .1       0  625.57    .045       0   655.2      .1       0
Bank Sta=625.57,655.2
XS Rating Curve= 0 ,0
Exp/Cntr(USF)=0,0
Exp/Cntr=0.3,0.1
LCMann Table=0

Chan Stop Cuts=-1
Use User Specified Reach Order=0
Composite Channel Slope=5